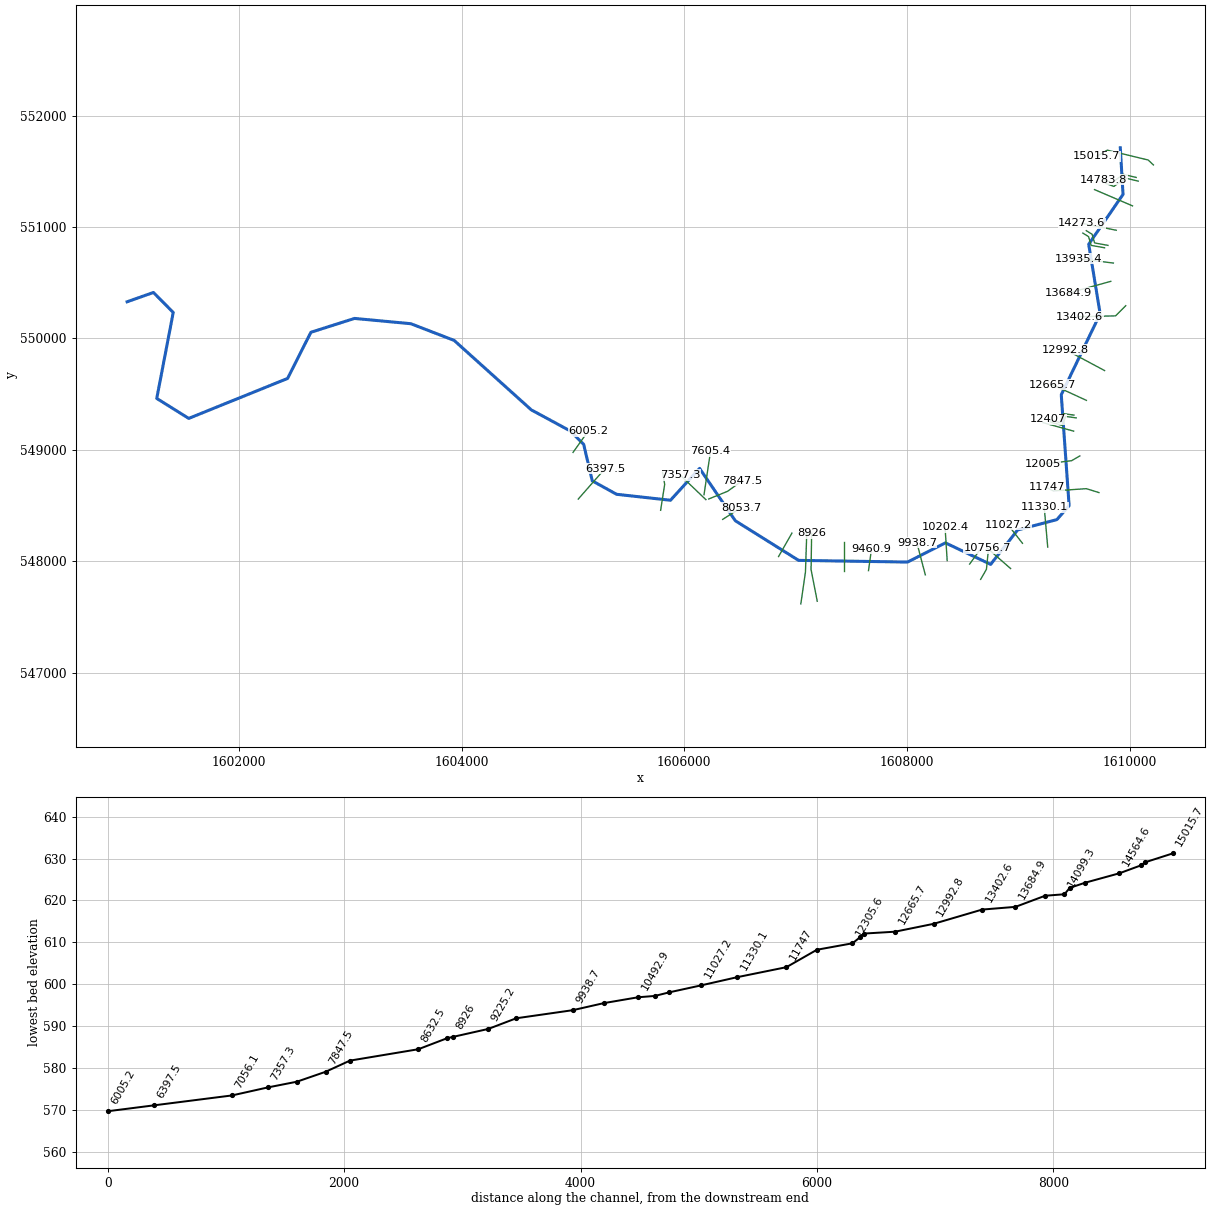
--- SevnmileCr.prj (project) ---

Proj Title=SevnmileCr
Current Plan=p01
Geom File=g01
Flow File=f01
Plan File=p01
DSS Export Rating Curves=0
DSS Export Rating Curve Sorted=0
DSS Export Volume Flow Curves=0
DXF OffsetX=0
DXF OffsetY=0
DXF ScaleX=0
DXF ScaleY=0

--- SevnmileCr.p01 (plan) ---

Plan Title=Floodplain
Program Version=4.00
Geom File=g01
Flow File=f01
K Sum by GR=0
Std Step Tol=0.01
Critical Tol=0.01
Num of Std Step Trials=20
Max Error Tol=0.3
Flow Tol Ratio=0.001
Split Flow NTrial=30
Split Flow Tol=0.02
Split Flow Ratio=0.02
Log Output Level=0
Friction Slope Method=1
Unsteady Friction Slope Method=2
Unsteady Bridges Friction Slope Method=1
Global Log Level=0
CheckData=False
Run HTab=0
Run UNet=0
Run PostProcess=0
UNET Theta=0
UNET Theta Warmup=0
UNET ZTol=0
UNET ZSATol=0
UNET MxIter=0
UNET MaxInSteps=0
UNET DtIC=0
UNET DtMin=0
UNET MaxCRTS=0
UNET WFStab=0
UNET SFStab=0
UNET WFX=0
UNET SFX=0
UNET DSS MLevel=0
UNET DZMax Abort=0
UNET Convert EG Bridges=0
UNET Use Existing IB Tables=0
UNET Froude Limit=0
UNET Froude Power=0
Write IC File=0
Echo Input=False
Echo Output=False
Write Detailed=0

--- SevnmileCr.f01 (steady flow) ---

Flow Title=NFF Regression Equation
Program Version=4.10
Number of Profiles= 1
Profile Names=P100yr
River Rch & RM=SevnmileCr,Main            ,15015.7
     727
River Rch & RM=SevnmileCr,Main            ,14273.6
     955
River Rch & RM=SevnmileCr,Main            ,13402.6
     988
River Rch & RM=SevnmileCr,Main            ,12407
    1041
River Rch & RM=SevnmileCr,Main            ,12005
    1053
River Rch & RM=SevnmileCr,Main            ,9225.2
    1151
River Rch & RM=SevnmileCr,Main            ,8632.5
    1059
River Rch & RM=SevnmileCr,Main            ,8053.7
    1281
River Rch & RM=SevnmileCr,Main            ,7605.4
    1291
River Rch & RM=SevnmileCr,Main            ,6397.5
    1407
River Rch & RM=SevnmileCr,Main            ,5075.5
    1425
River Rch & RM=SevnmileCr,Main            ,4502.4
    1440
River Rch & RM=SevnmileCr,Main            ,3878
    1448
River Rch & RM=SevnmileCr,Main            ,3395.2
    1476
River Rch & RM=SevnmileCr,Main            ,1689
    1502
River Rch & RM=SevnmileCr,Main            ,1500.4
    1503
River Rch & RM=SevnmileCr,Main            ,319.1
    1557
Boundary for River Rch & Prof#=SevnmileCr,Main            , 1
Up Type= 0
Dn Type= 3
Dn Slope=0.00509
DSS Import GetInterval= 0
DSS Import GetPeak= 0
DSS Import FillOption= 0

--- SevnmileCr.g01 (geometry) ---

Geom Title=USGS 10m DEM
Program Version=4.10

River Reach=SevnmileCr      ,Main
Reach XY= 30
     1609914.669      551710.739     1609939.141      551292.426
     1609630.989       550844.94     1609733.914      550221.255
     1609384.513      549495.042     1609455.195      548499.893
     1609345.603       548375.11     1608992.802       548281.91
     1608750.398      547973.143      1608344.53      548166.295
     1608004.252      547994.073     1607026.433      548009.089
     1606458.499      548364.193     1606137.069      548834.261
     1605875.628        548548.5     1605391.658      548602.004
     1605173.417      548722.766     1605096.613      549049.628
     1604975.623      549170.405     1604626.347      549359.197
     1603933.446      549982.401      1603544.53      550132.267
     1603038.844      550179.631     1602647.207      550055.273
     1602437.846      549641.178     1601550.353      549282.832
     1601263.275      549461.913     1601411.222      550232.959
     1601233.653      550412.433     1600997.055       550328.95

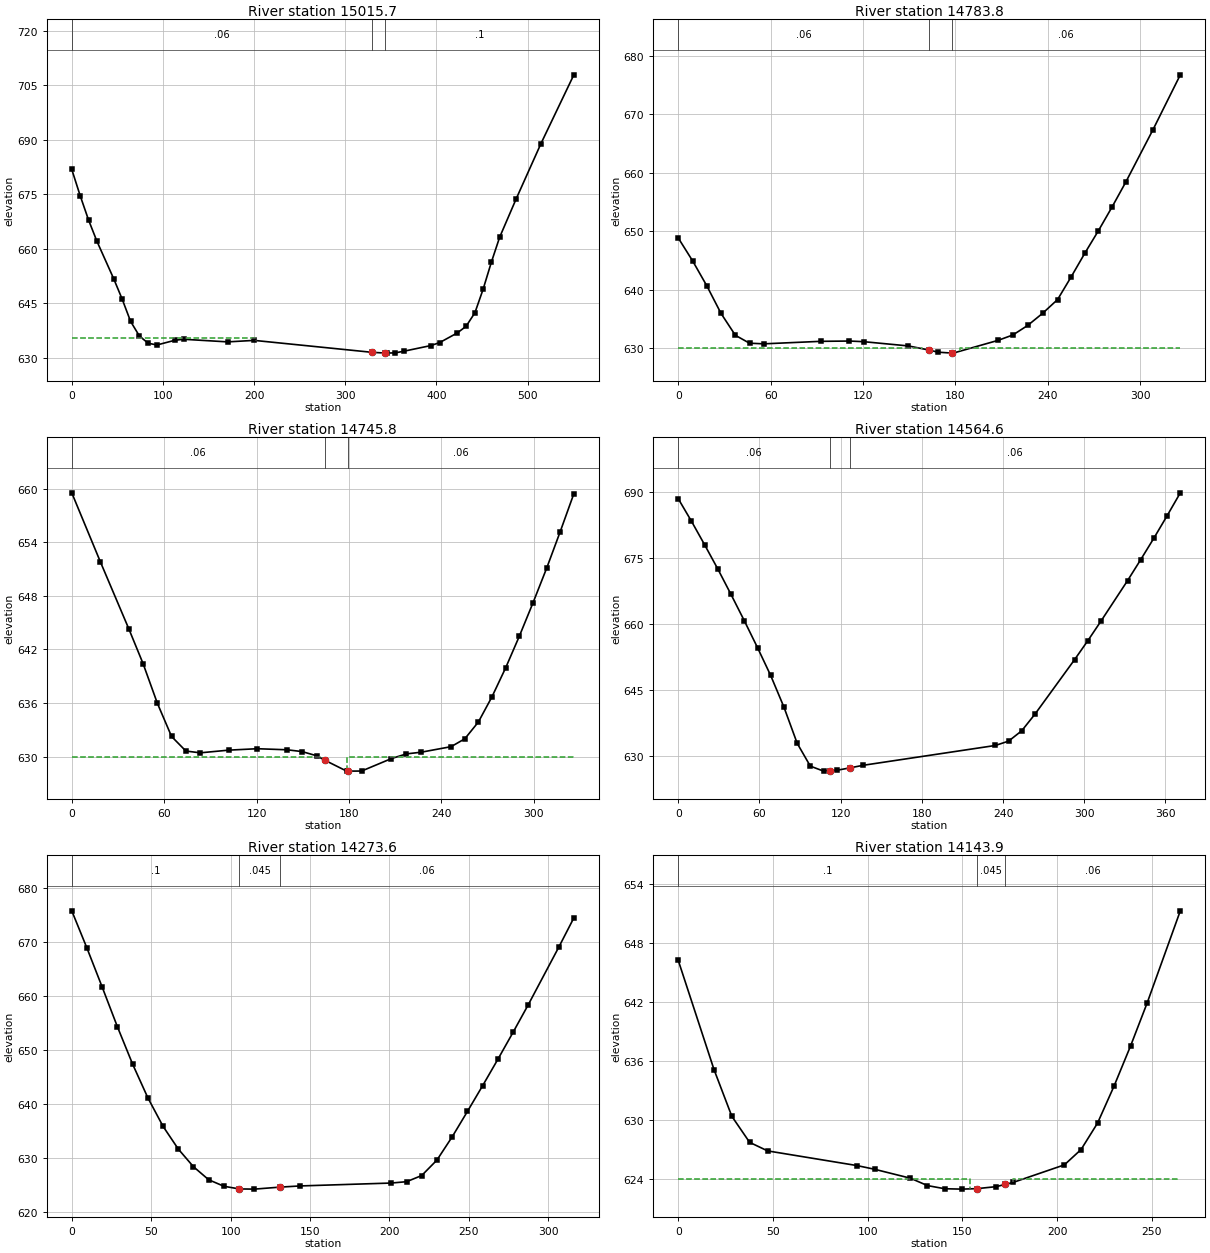
Type RM Length L Ch R = 1 ,15015.7 ,211.8,231.9,251.9
XS GIS Cut Line= 4
     1610211.882      551556.528     1610165.007      551600.799
     1609797.819      551689.341     1609704.069      551634.653
#Sta/Elev= 30
       0  681.83     9.2  674.62    18.4  667.91    27.6  662.04      46  651.72
    55.3   646.1    64.5  639.98    74.2  635.94    83.8  633.95    93.5  633.48
   112.9  634.76   122.6  635.05     171  634.33   200.1  634.74   329.1  631.46
   344.1  631.24   345.3  631.23     355  631.31   364.7  631.78   393.8  633.31
   403.4  634.12   422.8  636.78   432.5  638.62   442.2  642.36   451.2  648.85
   460.3  656.34   469.3  663.15   487.4  673.71   514.5  688.89   550.7   707.9
#Mann= 3 , 0 , 0
       0     .06       0   329.1    .045       0   344.1      .1       0
#XS Ineff= 2 , 0
          201.97  635.31
Permanent Ineff=
       F       F
Bank Sta=329.1,344.1
XS Rating Curve= 0 ,0
Exp/Cntr=0.3,0.1

Type RM Length L Ch R = 1 ,14783.8 ,38.3,37.9,38.2
XS GIS Cut Line= 4
     1610057.125      551444.411     1609939.937      551472.188
     1609839.243      551396.668      1609764.59      551424.445
#Sta/Elev= 27
       0  648.85     9.3  644.94    18.5  640.68    27.8  635.92    37.1  632.18
    46.3  630.83    55.6  630.72    92.6  631.15   111.2   631.2   120.4  631.09
   149.5  630.36   162.6  629.67   168.8  629.29   177.6  629.14   178.5  629.13
   207.6  631.31   217.3  632.24   226.9  633.87   236.6  635.95   246.3   638.3
   255.2  642.22     264  646.24   272.8  650.08   281.7  654.16   290.6  658.42
   308.3  667.41     326  676.78
#Mann= 3 , 0 , 0
       0     .06       0   162.6    .045       0   177.6     .06       0
#XS Ineff= 2 , 0
       0     158     630     183       0     630
Permanent Ineff=
       F       F
Bank Sta=162.6,177.6
XS Rating Curve= 0 ,0
Exp/Cntr=0.3,0.1

Type RM Length L Ch R = 1 ,14745.8 ,204.7,181.3,157.1
XS GIS Cut Line= 4
     1610075.354      551411.424     1609958.166      551439.202
     1609857.472      551363.681     1609782.819      551391.459
#Sta/Elev= 30
       0  659.54    18.5  651.84    37.1  644.28    46.3  640.41    55.6  635.96
    64.8  632.25    74.1  630.62    83.4  630.42   101.9  630.72   120.4  630.88
   139.8  630.76   149.5  630.56   159.2  630.08   164.2   629.6   178.5  628.37
   179.2  628.37   188.2  628.38   207.6  629.78   217.3   630.3   226.9  630.49
   246.3  631.11   255.2  631.99     264  633.87   272.8  636.68   281.7  639.93
   290.6  643.48   299.4  647.19   308.3  651.08   317.1  655.17     326  659.44
#Mann= 3 , 0 , 0
       0     .06       0   164.2    .045       0   179.2     .06       0
#XS Ineff= 2 , 0
       0     163     630     179       0     630
Permanent Ineff=
       F       F
Bank Sta=164.2,179.2
XS Rating Curve= 0 ,0
Exp/Cntr=0.3,0.1

Type RM Length L Ch R = 1 ,14564.6 ,285.1,291,296.8
XS GIS Cut Line= 2
     1610024.382      551189.341     1609683.236      551335.174
#Sta/Elev= 28
       0   688.5     9.8  683.36    19.5  678.01    29.3  672.47      39  666.71
    48.8  660.74    58.6  654.59    68.3  648.27    78.1  641.07    87.9  632.82
    97.6  627.63   107.4  626.49     112  626.58   117.2  626.68     127  627.24
   136.7  627.82   234.3  632.33   244.1  633.32   253.8  635.67   263.6  639.46
   292.9  651.88   302.7   656.2   312.4  660.65     332  669.85   341.7  674.61
   351.5  679.54   361.2   684.6     371  689.84
#Mann= 3 , 0 , 0
       0     .06       0     112    .045       0     127     .06       0
Bank Sta=112,127
XS Rating Curve= 0 ,0
Exp/Cntr=0.3,0.1

Type RM Length L Ch R = 1 ,14273.6 ,158.1,129.7,101.4
XS GIS Cut Line= 2
     1609878.549      550970.591     1609568.653      551033.091
#Sta/Elev= 27
       0  675.85     9.6  668.91    19.2  661.67    28.7  654.37    38.3  647.42
    47.9  641.17    57.5  635.86    67.1  631.65    76.6  628.39    86.2  625.97
    95.8  624.76   105.4  624.27     115  624.23     131   624.6   143.7  624.82
   201.2  625.36   210.8  625.61   220.3  626.75   229.9  629.62   239.5  633.93
   249.1  638.64   258.7  643.43   268.2  648.28   277.8   653.3   287.4  658.43
   306.6   669.1   316.1  674.54
#Mann= 3 , 0 , 0
       0      .1       0   105.4    .045       0     131     .06       0
Bank Sta=105.4,131
XS Rating Curve= 0 ,0
Exp/Cntr=0.3,0.1

Type RM Length L Ch R = 1 ,14143.9 ,45,44.6,44.5
XS GIS Cut Line= 4
      1609804.52      550835.036     1609683.861      550856.737
     1609661.291      550934.862     1609609.208       550966.98
#Sta/Elev= 22
       0  646.28    18.9  635.16    28.3  630.41    37.7  627.76    47.2  626.89
    94.3   625.4   103.7  625.02   122.6  624.11   131.6  623.36   140.7  623.04
   149.7     623   157.7  623.05   167.8  623.25   172.7  623.48   176.8  623.68
   203.9  625.47   212.7  627.03   221.4  629.72   230.1  633.48   238.9   637.6
   247.6  641.95   265.1  651.32
#Mann= 3 , 0 , 0
       0      .1       0   157.7    .045       0   172.7     .06       0
#XS Ineff= 2 , 0
       0     154     624     177       0     624
Permanent Ineff=
       F       F
Bank Sta=157.7,172.7
XS Rating Curve= 0 ,0
Exp/Cntr=0.3,0.1

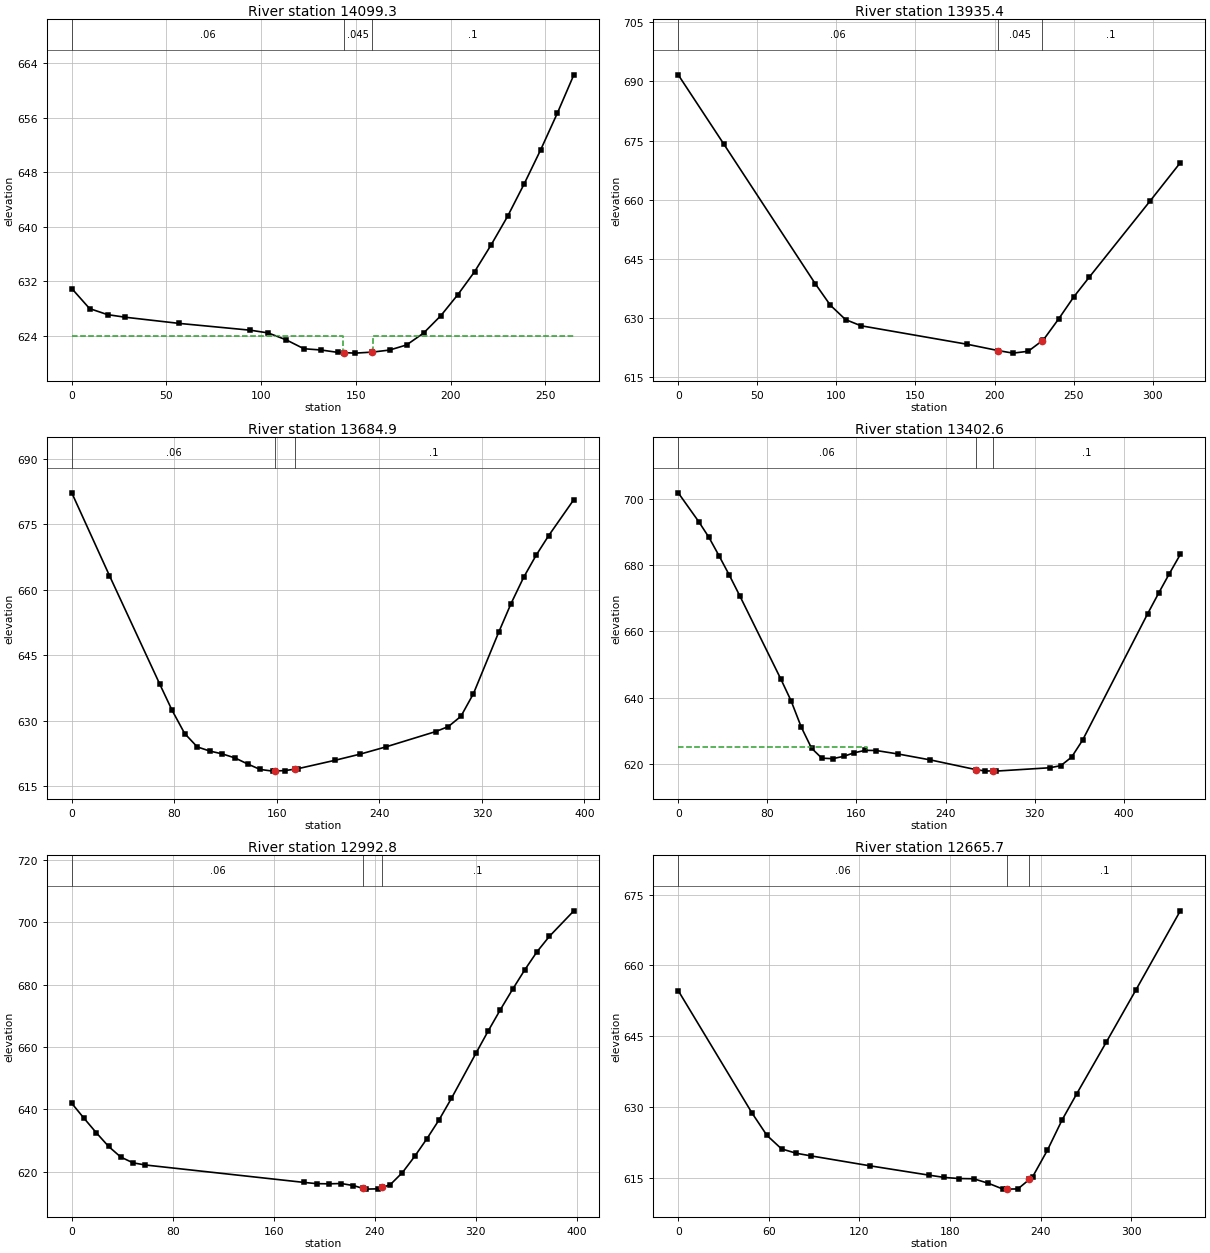
Type RM Length L Ch R = 1 ,14099.3 ,134,163.9,193.2
XS GIS Cut Line= 4
      1609773.27      550813.334     1609652.611      550835.036
     1609630.041      550913.161     1609577.958      550945.279
#Sta/Elev= 26
       0  630.95     9.4  628.01    18.9  627.12    28.3  626.74    56.6  625.84
    94.3  624.84   103.7  624.44   113.2  623.43   122.6  622.12   131.6  621.94
   140.7  621.58   143.7  621.55   149.7  621.48   158.7  621.63   167.8  621.93
   176.8  622.68   185.8  624.43   194.9  626.98   203.9  630.07   212.7  633.42
   221.4  637.33   230.1  641.52   238.9   646.3   247.6  651.29   256.4  656.66
   265.1  662.27
#Mann= 3 , 0 , 0
       0     .06       0   143.7    .045       0   158.7      .1       0
#XS Ineff= 2 , 0
       0     143     624     159       0     624
Permanent Ineff=
       F       F
Bank Sta=143.7,158.7
XS Rating Curve= 0 ,0
Exp/Cntr=0.3,0.1

Type RM Length L Ch R = 1 ,13935.4 ,241.1,250.6,259.9
XS GIS Cut Line= 2
     1609852.507       550676.32     1609537.403      550715.382
#Sta/Elev= 17
       0  691.65    28.9  674.05    86.6  638.74    96.2  633.26   105.8  629.62
   115.5  628.06   182.8  623.36   202.1  621.78   211.7  621.12   221.3  621.59
   229.9  624.17   230.9  624.47   240.5  629.75   250.2  635.41   259.8  640.31
   298.3  659.63   317.5  669.38
#Mann= 3 , 0 , 0
       0     .06       0   202.1    .045       0   229.9      .1       0
Bank Sta=202.1,229.9
XS Rating Curve= 0 ,0
Exp/Cntr=0.3,0.1

Type RM Length L Ch R = 1 ,13684.9 ,287.5,282.2,277.2
XS GIS Cut Line= 2
     1609829.069      550512.257     1609451.465      550408.091
#Sta/Elev= 29
       0  682.23    29.4  663.26    68.6  638.43    78.3  632.38    88.1  627.08
    97.9  624.02   107.7  623.07   117.5  622.41   127.3   621.5   137.1  620.12
   146.9  618.86   156.7  618.47   158.8   618.5   166.5   618.6   173.8  618.91
   176.3  619.02   205.6  620.97   225.2  622.38   244.8     624     284  627.54
   293.8  628.68   303.6  631.03   313.4  636.24     333  650.24   342.7  656.86
   352.5  662.85   362.3  667.94   372.1  672.44   391.7  680.68
#Mann= 3 , 0 , 0
       0     .06       0   158.8    .045       0   173.8      .1       0
Bank Sta=158.8,173.8
XS Rating Curve= 0 ,0
Exp/Cntr=0.3,0.1

Type RM Length L Ch R = 1 ,13402.6 ,421.8,409.9,397.7
XS GIS Cut Line= 3
     1609963.339      550293.836     1609872.193      550202.691
     1609550.424      550194.549
#Sta/Elev= 30
       0  701.75    18.4  693.06    27.6   688.3    36.8  682.66      46  676.84
    55.2  670.73    92.1   645.6   101.3  639.04   110.5  631.07   119.7  624.74
   128.9  621.73   138.6  621.57   148.4  622.27   158.2  623.37   167.9  624.09
   177.7  624.04   197.2     623   226.4   621.2   267.6  618.25   275.2  617.89
   282.6  617.84     285  617.82   333.7  618.84   343.5  619.47   353.2  622.05
     363  627.13   421.5  665.31   431.3  671.47     441   677.4   450.8  683.17
#Mann= 3 , 0 , 0
       0     .06       0   267.6    .045       0   282.6      .1       0
#XS Ineff= 2 , 0
          169.72  624.99
Permanent Ineff=
       F       F
Bank Sta=267.6,282.6
XS Rating Curve= 0 ,0
Exp/Cntr=0.3,0.1

Type RM Length L Ch R = 1 ,12992.8 ,325.7,327.1,328.4
XS GIS Cut Line= 2
     1609773.514       549711.91     1609422.819       549899.41
#Sta/Elev= 30
       0  641.95     9.7  637.16    19.4  632.53    29.1  628.15    38.8  624.71
    48.5  622.86    58.2  622.17   184.3  616.56     194  616.18   203.7  616.12
   213.4  616.22   223.1  615.56   230.9  614.64   232.8  614.42   242.5  614.52
   245.9  614.98   252.2  615.82   261.9  619.73   271.6  624.92   281.3  630.59
     291  636.69   300.7  643.52   320.1  657.99   329.8  665.14   339.5  672.01
   349.2  678.56   358.9  684.84   368.6  690.64   378.3  695.53   397.7  703.73
#Mann= 3 , 0 , 0
       0     .06       0   230.9    .045       0   245.9      .1       0
Bank Sta=230.9,245.9
XS Rating Curve= 0 ,0
Exp/Cntr=0.3,0.1

Type RM Length L Ch R = 1 ,12665.7 ,213,258.6,300.8
XS GIS Cut Line= 2
     1609610.319      549444.549     1609308.236      549583.438
#Sta/Elev= 23
       0  654.66    48.9  628.67    58.7  623.96    68.4  621.08    78.2  620.15
      88  619.59   127.1  617.48   166.2   615.5     176  615.03   185.8  614.79
   195.6  614.74   205.4  613.78   215.1  612.54   217.6  612.55   224.9  612.58
   232.6  614.61   234.7  615.16   244.5  620.81   254.2  627.22     264  632.83
   283.6   643.8   303.2  654.87   332.5   671.6
#Mann= 3 , 0 , 0
       0     .06       0   217.6    .045       0   232.6      .1       0
Bank Sta=217.6,232.6
XS Rating Curve= 0 ,0
Exp/Cntr=0.3,0.1

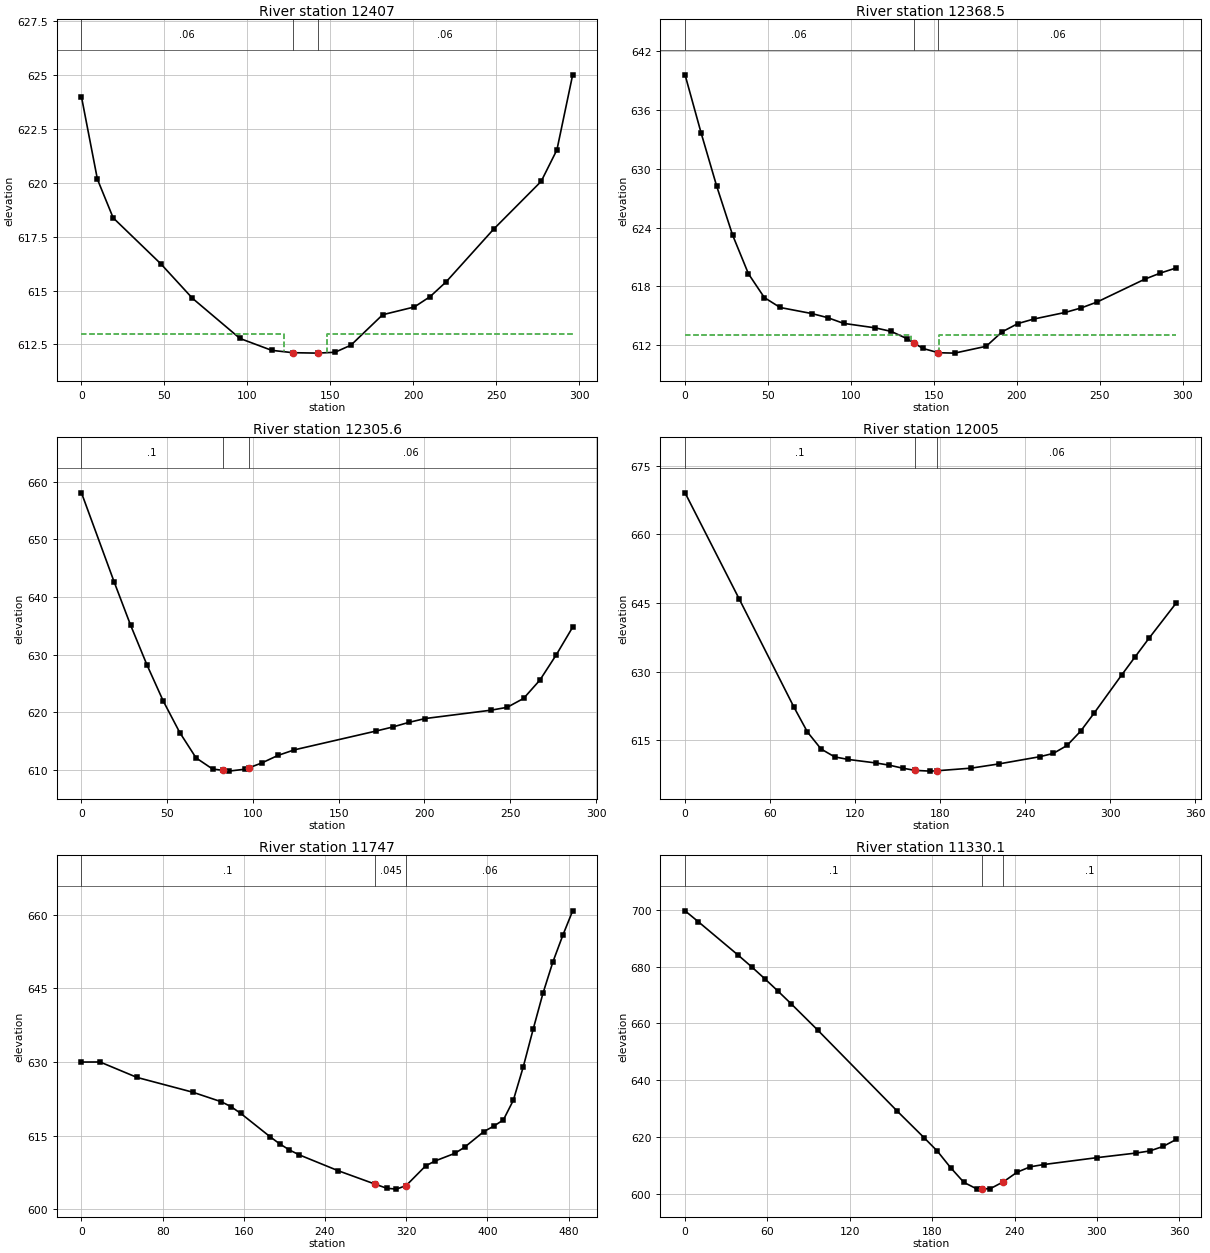
Type RM Length L Ch R = 1 ,12407   ,42.3,38.5,40.1
XS GIS Cut Line= 4
     1609498.965      549312.466     1609404.347      549325.487
     1609374.833      549244.758      1609264.59      549276.008
#Sta/Elev= 19
       0  623.98     9.6  620.16    19.1  618.37    47.8  616.24    66.9  614.64
    95.5  612.78   114.6  612.23   127.4  612.12   142.4   612.1   152.8  612.14
   162.4  612.47   181.5  613.88   200.6  614.24   210.1  614.72   219.7   615.4
   248.3  617.84     277  620.06   286.5  621.52     296     625
#Mann= 3 , 0 , 0
       0     .06       0   127.4    .045       0   142.4     .06       0
#XS Ineff= 2 , 0
       0     122     613     148       0     613
Permanent Ineff=
       F       F
Bank Sta=127.4,142.4
XS Rating Curve= 0 ,0
Exp/Cntr=0.3,0.1

Type RM Length L Ch R = 1 ,12368.5 ,101.5,62.9,22.8
XS GIS Cut Line= 4
      1609518.93      549287.293     1609424.312      549300.313
     1609394.798      549219.584     1609284.555      549250.834
#Sta/Elev= 27
       0   639.6     9.6  633.71    19.1  628.21    28.6  623.26    38.2  619.28
    47.8  616.85    57.3  615.84    76.4  615.22      86   614.8    95.5  614.22
   114.6  613.76   124.2   613.4   133.7  612.66   137.7  612.24   143.3  611.66
   152.7  611.22   162.4  611.18   181.5  611.88     191  613.35   200.6   614.2
   210.1  614.66   229.2  615.34   238.8   615.8   248.3   616.4     277  618.73
   286.5  619.36     296  619.88
#Mann= 3 , 0 , 0
       0     .06       0   137.7    .045       0   152.7     .06       0
#XS Ineff= 2 , 0
       0     136     613     153       0     613
Permanent Ineff=
       F       F
Bank Sta=137.7,152.7
XS Rating Curve= 0 ,0
Exp/Cntr=0.3,0.1

Type RM Length L Ch R = 1 ,12305.6 ,291.7,300.6,309.1
XS GIS Cut Line= 2
     1609495.736      549168.507     1609219.694      549244.896
#Sta/Elev= 25
       0  658.06    19.1  642.56    28.6  635.13    38.2  628.19    47.7  621.92
    57.3  616.47    66.8  612.07    76.4  610.14    82.4  609.91    85.9  609.77
    95.5  610.11    97.4  610.32     105  611.17   114.6   612.5   124.1  613.46
   171.8  616.73   181.4  617.42   190.9  618.23   200.5   618.9   238.7  620.34
   248.2  620.84   257.8  622.39   267.3  625.57   276.9  629.98   286.4  634.75
#Mann= 3 , 0 , 0
       0      .1       0    82.4    .045       0    97.4     .06       0
Bank Sta=82.4,97.4
XS Rating Curve= 0 ,0
Exp/Cntr=0.3,0.1

Type RM Length L Ch R = 1 ,12005   ,258.5,258.1,256.3
XS GIS Cut Line= 3
     1609551.292      548946.285     1609476.639      548902.882
     1609217.958      548873.369
#Sta/Elev= 24
       0  669.11    38.4  645.78    76.8  622.26    86.4  616.78      96  613.07
   105.6  611.34   115.3  610.78   134.6  610.02   144.2  609.53   153.8  608.86
   162.5  608.39   173.1  608.23   177.5   608.3   202.1  608.89   221.4   609.8
   250.3  611.38   259.9   612.1   269.6  613.84   279.2  616.97   288.8  620.95
   308.1  629.23   317.8  633.29   327.4  637.27   346.7  645.02
#Mann= 3 , 0 , 0
       0      .1       0   162.5    .045       0   177.5     .06       0
Bank Sta=162.5,177.5
XS Rating Curve= 0 ,0
Exp/Cntr=0.3,0.1

Type RM Length L Ch R = 1 ,11747   ,452.6,416.9,381.7
XS GIS Cut Line= 4
     1609723.141      548617.123      1609609.75      548652.538
     1609313.444      548632.049      1609252.68      548663.299
#Sta/Elev= 30
       0  629.98    18.3  629.99    54.8  626.84   109.7  623.83     138  621.87
   147.5  620.87   157.1  619.49   185.9  614.75   195.4  613.29     205  612.05
   214.6  611.06   252.9  607.83   289.1  605.11   300.8  604.25   310.4  604.07
     320   604.8   339.2  608.81   348.7  609.83   367.9  611.36   377.5   612.6
   396.6  615.81   406.2   616.9   415.8  618.18   425.6  622.18   435.3  628.92
   445.1  636.62   454.8  643.98   464.6  650.39   474.4  655.83   484.1  660.81
#Mann= 3 , 0 , 0
       0      .1       0   289.1    .045       0     320     .06       0
Bank Sta=289.1,320
XS Rating Curve= 0 ,0
Exp/Cntr=0.3,0.1

Type RM Length L Ch R = 1 ,11330.1 ,289.9,302.9,316
XS GIS Cut Line= 2
     1609262.905      548127.993     1609231.847       548484.48
#Sta/Elev= 26
       0  699.59     9.7  695.74    38.7  683.99    48.4  679.93      58  675.73
    67.7  671.34    77.4  666.83    96.7   657.6   154.7  629.05   174.1  619.78
   183.8  615.04   193.4  609.25   203.1  604.06   212.8  601.68   216.3  601.75
   222.4  601.86   231.3  604.12   232.1  604.32   241.8  607.62   251.4  609.53
   261.1  610.32   299.8  612.74   328.8  614.39   338.5  615.11   348.2   616.7
   357.8  619.16
#Mann= 3 , 0 , 0
       0      .1       0   216.3    .045       0   231.3      .1       0
Bank Sta=216.3,231.3
XS Rating Curve= 0 ,0
Exp/Cntr=0.3,0.1

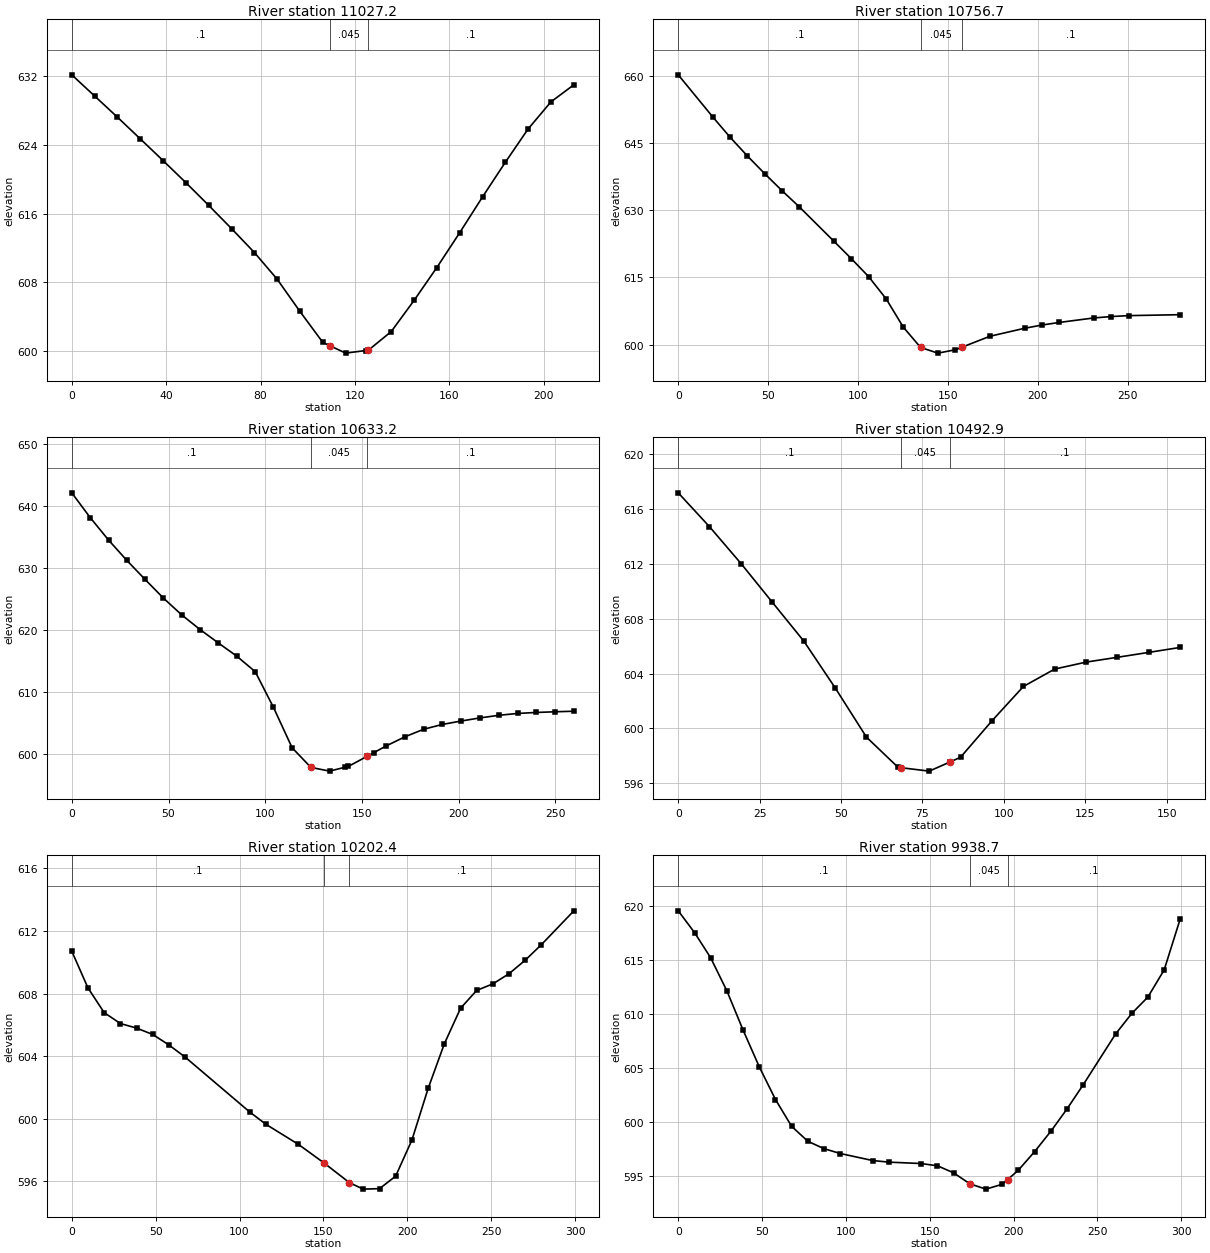
Type RM Length L Ch R = 1 ,11027.2 ,266.3,270.5,274.6
XS GIS Cut Line= 2
     1609036.345      548162.217     1608905.458      548329.966
#Sta/Elev= 25
       0  632.16     9.7  629.69    19.3  627.24      29  624.71    38.7  622.17
    48.4  619.59      58  616.96    67.7  614.25    77.4  611.46      87  608.37
    96.7   604.6   106.4  600.99   109.5  600.59   116.1  599.74   124.5  600.04
   125.7  600.08   135.4  602.25   145.1  605.89   154.7   609.7   164.4  613.76
   174.1  617.94   183.8  621.99   193.4  625.85   203.1  629.01   212.8     631
#Mann= 3 , 0 , 0
       0      .1       0   109.5    .045       0   125.7      .1       0
Bank Sta=109.5,125.7
XS Rating Curve= 0 ,0
Exp/Cntr=0.3,0.1

Type RM Length L Ch R = 1 ,10756.7 ,145.8,123.5,101.2
XS GIS Cut Line= 2
     1608929.764      547935.869     1608719.388      548119.507
#Sta/Elev= 24
       0  660.33    19.3  650.86    28.9  646.34    38.5  642.16    48.2  638.17
    57.8  634.38    67.4  630.76    86.7  623.05    96.3  619.19   105.9  615.17
   115.6  610.22   125.2  603.86   134.8  599.33   144.4  598.07   154.1  598.82
   157.8   599.4   173.3  601.84   192.6  603.63   202.2  604.35   211.8  604.93
   231.1  605.94   240.7  606.25   250.4  606.46   279.2  606.67
#Mann= 3 , 0 , 0
       0      .1       0   134.8    .045       0   157.8      .1       0
Bank Sta=134.8,157.8
XS Rating Curve= 0 ,0
Exp/Cntr=0.3,0.1

Type RM Length L Ch R = 1 ,10633.2 ,153.2,140.4,127.3
XS GIS Cut Line= 3
     1608660.667      547838.646      1608712.75      547928.924
     1608728.375      548083.438
#Sta/Elev= 30
       0  642.17     9.5  638.18      19  634.54    28.4  631.27    37.9  628.17
    47.4  625.15    56.8  622.45    66.3  620.08    75.8   617.9    85.3  615.77
    94.8  613.28   104.2  607.53   113.9  600.97   123.6   597.8   133.3   597.2
   141.2  597.83     143  597.97   152.8  599.62   156.2   600.2   162.5  601.27
   172.2  602.75   181.9  603.97   191.6  604.75   201.3   605.3     211   605.8
   220.7  606.22   230.4  606.52   240.1  606.68   249.8  606.79   259.5  606.88
#Mann= 3 , 0 , 0
       0      .1       0   123.6    .045       0   152.8      .1       0
Bank Sta=123.6,152.8
XS Rating Curve= 0 ,0
Exp/Cntr=0.3,0.1

Type RM Length L Ch R = 1 ,10492.9 ,274.8,290.4,306.3
XS GIS Cut Line= 2
     1608561.708      547975.799     1608651.986      548100.799
#Sta/Elev= 19
       0  617.18     9.6  614.71    19.3  612.02    28.9   609.2    38.6  606.36
    48.2  602.96    57.8  599.37    67.5  597.17    68.4  597.14    77.1  596.89
    83.4  597.55    86.7   597.9    96.4  600.57     106  603.06   115.6  604.33
   125.3  604.84   134.9  605.19   144.6  605.55   154.2  605.91
#Mann= 3 , 0 , 0
       0      .1       0    68.4    .045       0    83.4      .1       0
Bank Sta=68.4,83.4
XS Rating Curve= 0 ,0
Exp/Cntr=0.3,0.1

Type RM Length L Ch R = 1 ,10202.4 ,259.5,263.8,268.1
XS GIS Cut Line= 2
     1608360.319      548007.049     1608341.222       548305.66
#Sta/Elev= 26
       0  610.71     9.6  608.37    19.3  606.78      29  606.08    38.6  605.79
    48.3  605.38    57.9  604.71    67.6  603.93   106.2  600.41   115.8  599.63
   135.1  598.35   150.5  597.15   165.5   595.9   173.7  595.49   183.4  595.52
     193  596.32   202.7  598.63   212.4  601.94     222  604.78   231.7  607.06
   241.3   608.2     251  608.62   260.6  609.27   270.3  610.14   279.9  611.13
   299.2  613.29
#Mann= 3 , 0 , 0
       0      .1       0   150.5    .045       0   165.5      .1       0
Bank Sta=150.5,165.5
XS Rating Curve= 0 ,0
Exp/Cntr=0.3,0.1

Type RM Length L Ch R = 1 ,9938.7  ,486.8,477.8,468.6
XS GIS Cut Line= 2
     1608164.152       547878.98      1608087.75      548168.507
#Sta/Elev= 30
       0  619.58     9.7  617.57    19.3  615.24      29  612.17    38.6  608.56
    48.3  605.14      58   602.1    67.6  599.62    77.3  598.23    86.9  597.55
    96.6   597.1   115.9  596.45   125.6   596.3   144.9  596.17   154.6  595.96
   164.2  595.31   173.9  594.29   183.5   593.8   193.2  594.25   196.4  594.68
   202.8  595.55   212.5  597.27   222.2  599.16   231.8  601.22   241.5  603.47
   260.8  608.17   270.5  610.08   280.1   611.6   289.8  614.12   299.4  618.86
#Mann= 3 , 0 , 0
       0      .1       0   173.9    .045       0   196.4      .1       0
Bank Sta=173.9,196.4
XS Rating Curve= 0 ,0
Exp/Cntr=0.3,0.1

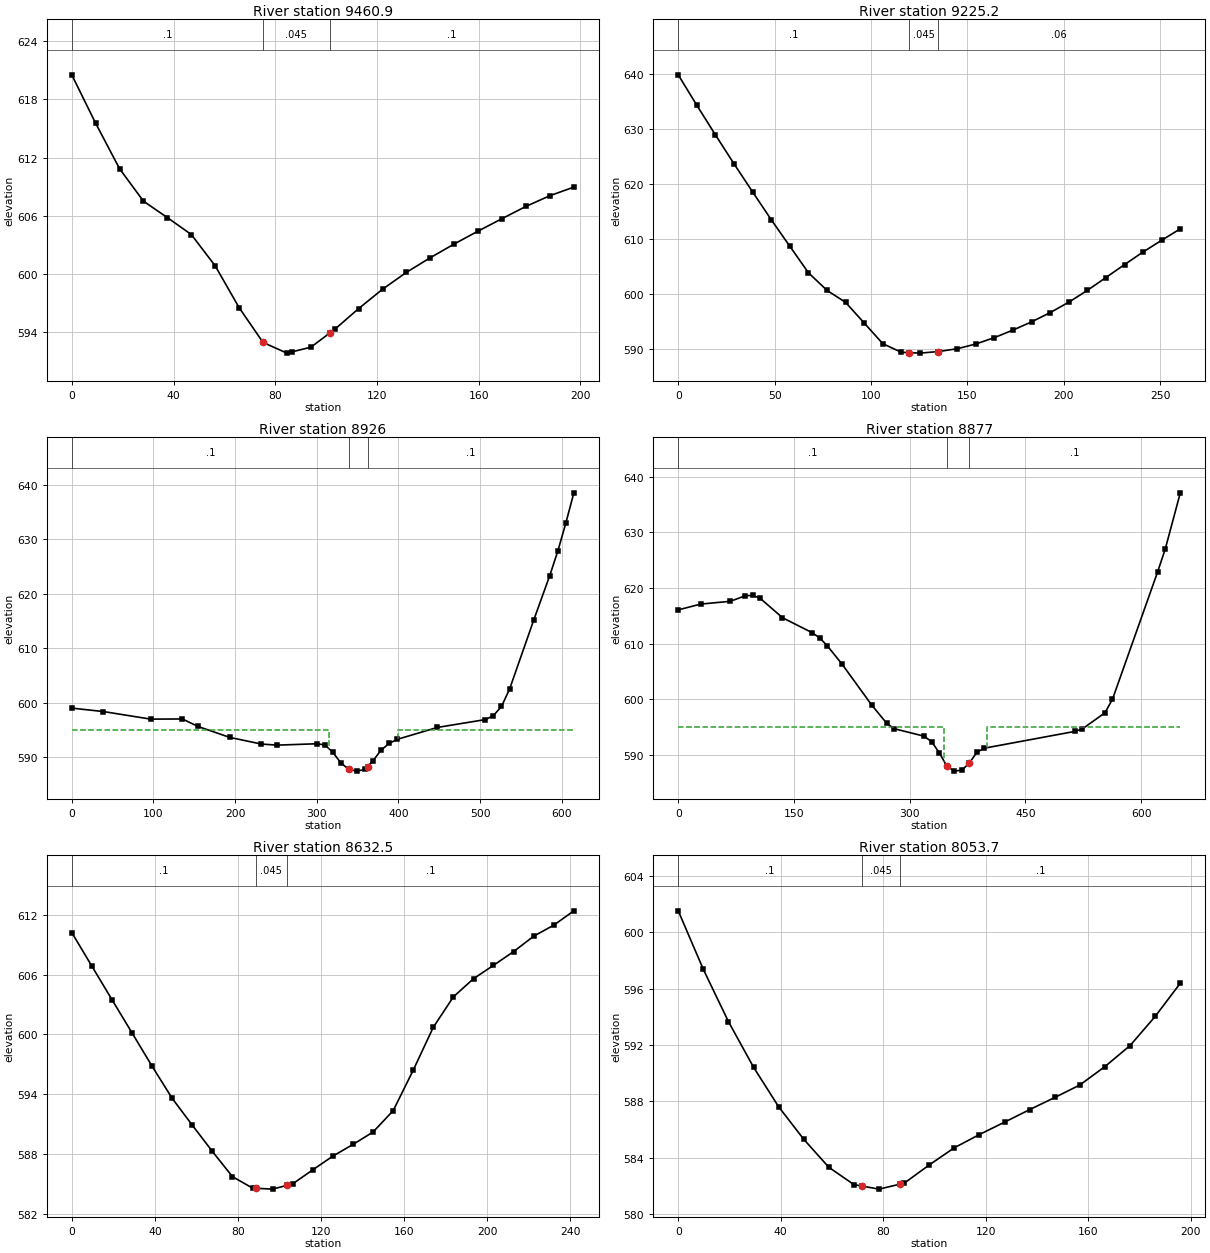
Type RM Length L Ch R = 1 ,9460.9  ,232.6,235.7,238.8
XS GIS Cut Line= 2
     1607653.874      547917.194     1607680.849      548112.763
#Sta/Elev= 24
       0  620.52     9.4  615.53    18.8  610.85    28.2  607.51    37.6  605.82
      47  604.08    56.4  600.85    65.8  596.55    75.2  592.97    84.6  591.87
    86.4  591.99      94  592.48   101.4  593.93   103.4  594.32   112.8  596.46
   122.2  598.45   131.6  600.19     141   601.7   150.4  603.11   159.8  604.44
   169.2  605.72   178.6  606.98     188  608.08   197.4  608.96
#Mann= 3 , 0 , 0
       0      .1       0    75.2    .045       0   101.4      .1       0
Bank Sta=75.2,101.4
XS Rating Curve= 0 ,0
Exp/Cntr=0.3,0.1

Type RM Length L Ch R = 1 ,9225.2  ,299.5,299.2,298.8
XS GIS Cut Line= 2
     1607433.236      547911.563     1607433.236       548171.98
#Sta/Elev= 30
       0  639.82     9.6  634.32    19.3  628.92    28.9  623.69    38.6  618.57
    48.2  613.55    57.9  608.71    67.5  603.92    77.2   600.7    86.8  598.54
    96.4  594.81   106.1  591.04   115.7  589.49   119.7  589.42   125.4  589.33
   134.7  589.61     135  589.62   144.7  590.13   154.3  590.98     164  592.15
   173.6  593.51   183.3  595.01   192.9  596.68   202.6  598.58   212.2  600.72
   221.8  603.04   231.5   605.4   241.1  607.68   250.8  609.82   260.4  611.89
#Mann= 3 , 0 , 0
       0      .1       0   119.7    .045       0   134.7     .06       0
Bank Sta=119.7,134.7
XS Rating Curve= 0 ,0
Exp/Cntr=0.3,0.1

Type RM Length L Ch R = 1 ,8926    ,49.4,49,48.6
XS GIS Cut Line= 3
     1607193.653      547642.466     1607138.097      547927.188
     1607143.305      548251.841
#Sta/Elev= 30
       0  598.99    38.7  598.36    96.7  596.97   135.4     597   154.7  595.62
   193.4  593.62   232.1   592.4   251.4   592.2   299.9  592.45   309.8  592.25
   319.6   590.9   329.4  588.95   339.3  587.75   349.1  587.43     359  587.74
   362.2  588.26   368.8  589.32   378.6  591.26   388.5   592.5   398.3  593.25
   447.5  595.44   506.6  596.89   516.4  597.63   526.2   599.3   536.1  602.48
   565.6  615.11   585.3  623.31   595.1  627.76     605  632.95   614.8  638.49
#Mann= 3 , 0 , 0
       0      .1       0   339.3    .045       0   362.2      .1       0
#XS Ineff= 2 , 0
       0     315     595     400       0     595
Permanent Ineff=
       F       F
Bank Sta=339.3,362.2
XS Rating Curve= 0 ,0
Exp/Cntr=0.3,0.1

Type RM Length L Ch R = 1 ,8877    ,255.6,244.5,233.4
XS GIS Cut Line= 3
     1607046.083       547618.16      1607087.75      547904.619
     1607099.903       548265.73
#Sta/Elev= 30
       0  616.06      29   617.1    67.5   617.6    86.8  618.59    96.5  618.66
   106.1  618.15   135.1  614.66   173.7  611.96   183.3  611.03     193  609.65
   212.3  606.33   250.9  598.96   270.2  595.71   279.8  594.74   318.8  593.39
   328.5  592.39   338.3  590.44   348.1  588.04   357.8  587.12   367.6   587.3
   377.4  588.57   387.1  590.51   396.9  591.24   514.1  594.25   523.8  594.69
   553.1  597.59   562.9  600.03   621.5  622.92   631.3     627   650.8  637.07
#Mann= 3 , 0 , 0
       0      .1       0   348.1    .045       0   377.4      .1       0
#XS Ineff= 2 , 0
       0     345     595     400       0     595
Permanent Ineff=
       F       F
Bank Sta=348.1,377.4
XS Rating Curve= 0 ,0
Exp/Cntr=0.3,0.1

Type RM Length L Ch R = 1 ,8632.5  ,589,578.7,567
XS GIS Cut Line= 2
      1606846.43      548043.507     1606966.222      548253.577
#Sta/Elev= 28
       0  610.23     9.7  606.85    19.4  603.48      29  600.17    38.7  596.81
    48.4  593.58      58  590.91    67.7  588.27    77.4  585.73    87.1  584.58
    88.5  584.57    96.7  584.48   103.5  584.85   106.4  585.01   116.1  586.42
   125.8   587.8   135.4  588.96   145.1  590.21   154.8  592.36   164.4   596.4
   174.1  600.72   183.8  603.78   193.5   605.6   203.1  606.94   212.8  608.32
   222.5  609.87   232.2  610.98   241.8  612.41
#Mann= 3 , 0 , 0
       0      .1       0    88.5    .045       0   103.5      .1       0
Bank Sta=88.5,103.5
XS Rating Curve= 0 ,0
Exp/Cntr=0.3,0.1

Type RM Length L Ch R = 1 ,8053.7  ,210.6,206.3,202.1
XS GIS Cut Line= 2
     1606344.694      548376.841     1606509.625      548482.744
#Sta/Elev= 23
       0  601.53     9.8  597.37    19.6  593.66    29.4  590.42    39.2  587.61
      49   585.3    58.8  583.31    68.6  582.08    71.7  581.98    78.4  581.76
    86.7  582.12    88.2  582.18      98  583.48   107.8   584.7   117.6  585.64
   127.4  586.52   137.2  587.41     147  588.27   156.8  589.16   166.6  590.47
   176.4  591.96   186.2  594.03     196  596.39
#Mann= 3 , 0 , 0
       0      .1       0    71.7    .045       0    86.7      .1       0
Bank Sta=71.7,86.7
XS Rating Curve= 0 ,0
Exp/Cntr=0.3,0.1

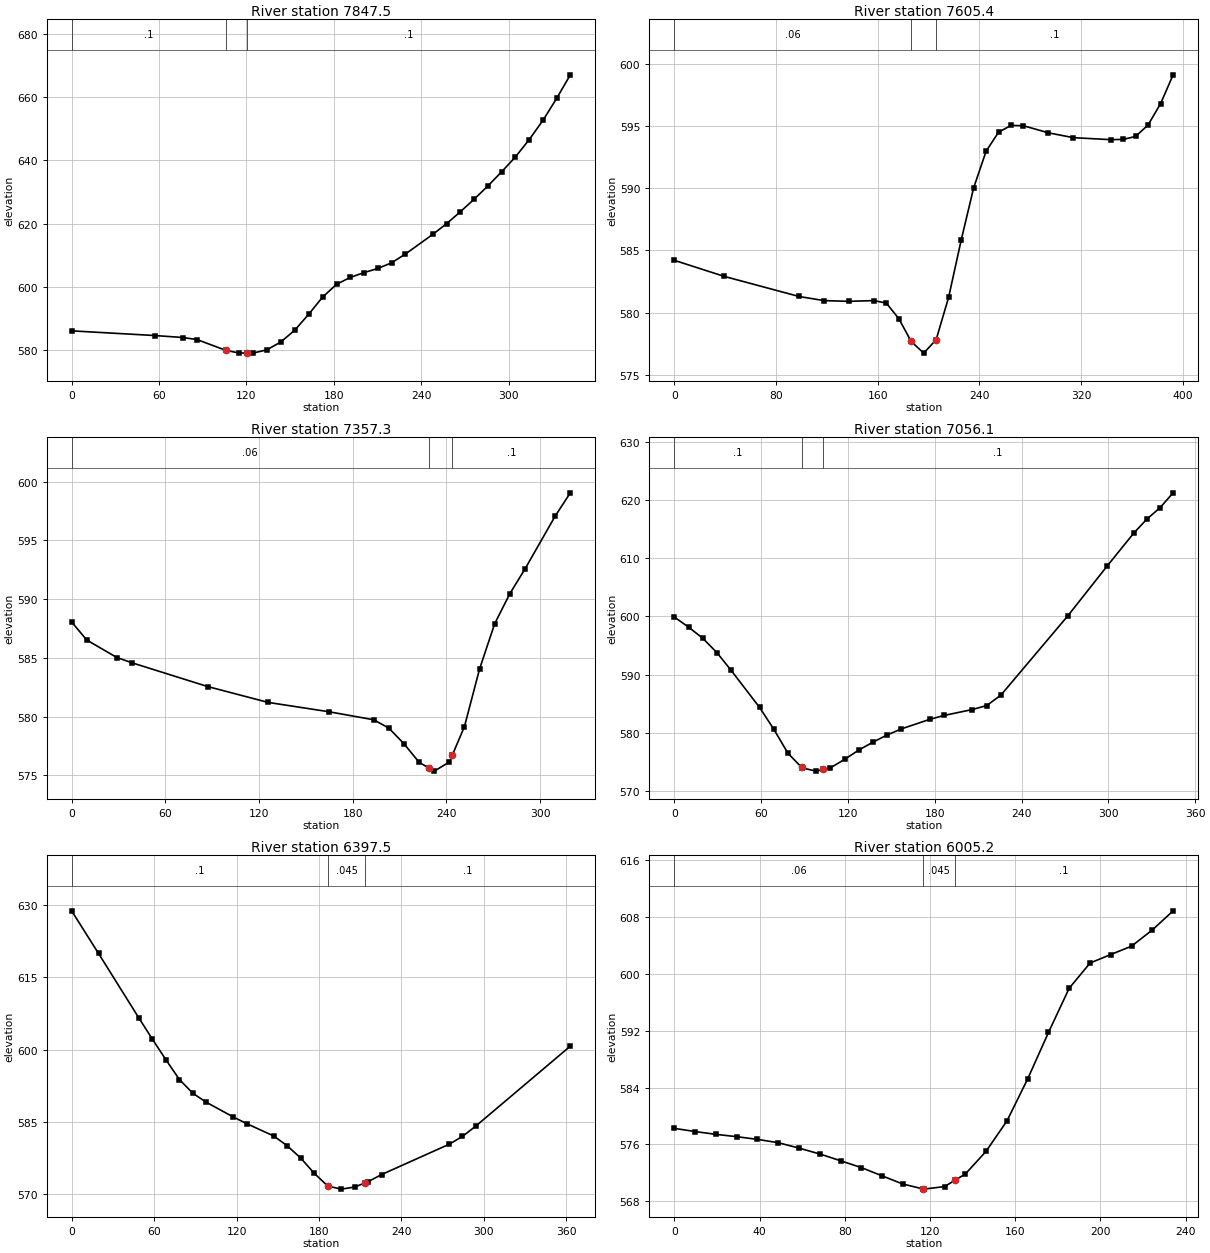
Type RM Length L Ch R = 1 ,7847.5  ,217.5,242.1,265.7
XS GIS Cut Line= 3
     1606219.701      548560.099     1606388.097      548628.577
     1606518.305      548722.327
#Sta/Elev= 30
       0  586.13    57.4  584.64    76.5  584.02    86.1  583.37   105.6     580
   114.8  579.13   120.6  579.11   124.4  579.09     134  580.14   143.5   582.6
   153.1  586.33   162.6  591.34   172.2  596.78   181.8  600.84   191.2  603.02
   200.7  604.54   210.1  605.84   219.5  607.62     229  610.39   247.8  616.61
   257.3  619.99   266.7  623.75   276.2  627.73   285.6   631.9     295  636.35
   304.5  641.07   313.9  646.51   323.4  652.63   332.8  659.58   342.2  667.03
#Mann= 3 , 0 , 0
       0      .1       0   105.6    .045       0   120.6      .1       0
Bank Sta=105.6,120.6
XS Rating Curve= 0 ,0
Exp/Cntr=0.3,0.1

Type RM Length L Ch R = 1 ,7605.4  ,226.6,248.2,270.6
XS GIS Cut Line= 2
     1606176.991      548598.314     1606235.319      548986.216
#Sta/Elev= 26
       0   584.2    39.2  582.91    98.1  581.29   117.7  580.96   137.3   580.9
   156.9  580.96   166.7  580.76   176.5  579.51   186.3  577.67   196.1  576.73
   205.9  577.81   215.7  581.22   225.6  585.83   235.4  590.04   245.2  592.99
     255  594.52   264.8  595.07   274.6  595.04   294.2  594.47   313.8  594.08
   343.2  593.92     353  593.94   362.8  594.18   372.6   595.1   382.5  596.83
   392.3  599.14
#Mann= 3 , 0 , 0
       0     .06       0   186.3    .045       0   205.9      .1       0
Bank Sta=186.3,205.9
XS Rating Curve= 0 ,0
Exp/Cntr=0.3,0.1

Type RM Length L Ch R = 1 ,7357.3  ,323.3,301.2,279
XS GIS Cut Line= 2
     1606193.653      548553.924      1605962.75       548774.41
#Sta/Elev= 22
       0  588.05     9.7  586.51      29  585.02    38.7  584.57    87.1  582.55
   125.8   581.2   164.5  580.41   193.5  579.72   203.2     579   212.8  577.68
   222.5   576.1   228.8  575.61   232.2  575.35   241.9  576.13   243.8  576.73
   251.5  579.14   261.2  584.05   270.9  587.91   280.6  590.46   290.2  592.54
   309.6  597.06   319.3  599.04
#Mann= 3 , 0 , 0
       0     .06       0   228.8    .045       0   243.8      .1       0
Bank Sta=228.8,243.8
XS Rating Curve= 0 ,0
Exp/Cntr=0.3,0.1

Type RM Length L Ch R = 1 ,7056.1  ,671.2,658.6,646
XS GIS Cut Line= 3
     1605787.403      548458.438     1605823.861      548691.077
     1605804.764      548798.716
#Sta/Elev= 29
       0  599.88     9.8  598.16    19.6  596.25    29.4  593.78    39.2  590.75
    58.9  584.38    68.7  580.65    78.5  576.52      88  574.08    88.3     574
    98.1  573.45     103  573.74   107.9  574.02   117.7  575.47   127.6  577.08
   137.4  578.44   147.2  579.67     157   580.7   176.6  582.34   186.4     583
     206  584.02   215.9   584.7   225.7  586.48   271.9  600.06   299.2  608.64
   317.5  614.26   326.6  616.68   335.7  618.63   344.8   621.2
#Mann= 3 , 0 , 0
       0      .1       0      88    .045       0     103      .1       0
Bank Sta=88,103
XS Rating Curve= 0 ,0
Exp/Cntr=0.3,0.1

Type RM Length L Ch R = 1 ,6397.5  ,389.9,392.3,394.7
XS GIS Cut Line= 2
     1605047.819      548559.132     1605287.403      548831.702
#Sta/Elev= 24
       0  628.82    19.6  619.98      49  606.57    58.8  602.19    68.7  597.89
    78.5  593.81    88.3  590.96    98.1  589.09   117.7  586.05   127.5  584.66
   147.1  582.11   156.9  580.08   166.7  577.54   176.5  574.39   186.4  571.73
   196.2  571.09     206  571.52   213.7  572.41   215.8  572.65   225.6  574.12
   274.6  580.38   284.4  582.02   294.2  584.19   362.9  600.75
#Mann= 3 , 0 , 0
       0      .1       0   186.4    .045       0   213.7      .1       0
Bank Sta=186.4,213.7
XS Rating Curve= 0 ,0
Exp/Cntr=0.3,0.1

Type RM Length L Ch R = 1 ,6005.2  ,151.2,150.8,150.4
XS GIS Cut Line= 2
     1605000.944      548977.535     1605136.361      549168.507
#Sta/Elev= 27
       0  578.24     9.8  577.79    19.5   577.4    29.3  577.07      39  576.69
    48.8  576.22    58.5  575.46    68.3  574.63      78  573.68    87.8  572.71
    97.6  571.54   107.3  570.39   116.6  569.72   117.1  569.68   126.8  570.04
   131.6  570.91   136.6  571.82   146.3  575.01   156.1  579.29   165.8  585.19
   175.6  591.76   185.3  597.98   195.1  601.54   204.8  602.74   214.6  603.92
   224.4  606.22   234.1   608.9
#Mann= 3 , 0 , 0
       0     .06       0   116.6    .045       0   131.6      .1       0
Bank Sta=116.6,131.6
XS Rating Curve= 0 ,0
Exp/Cntr=0.3,0.1