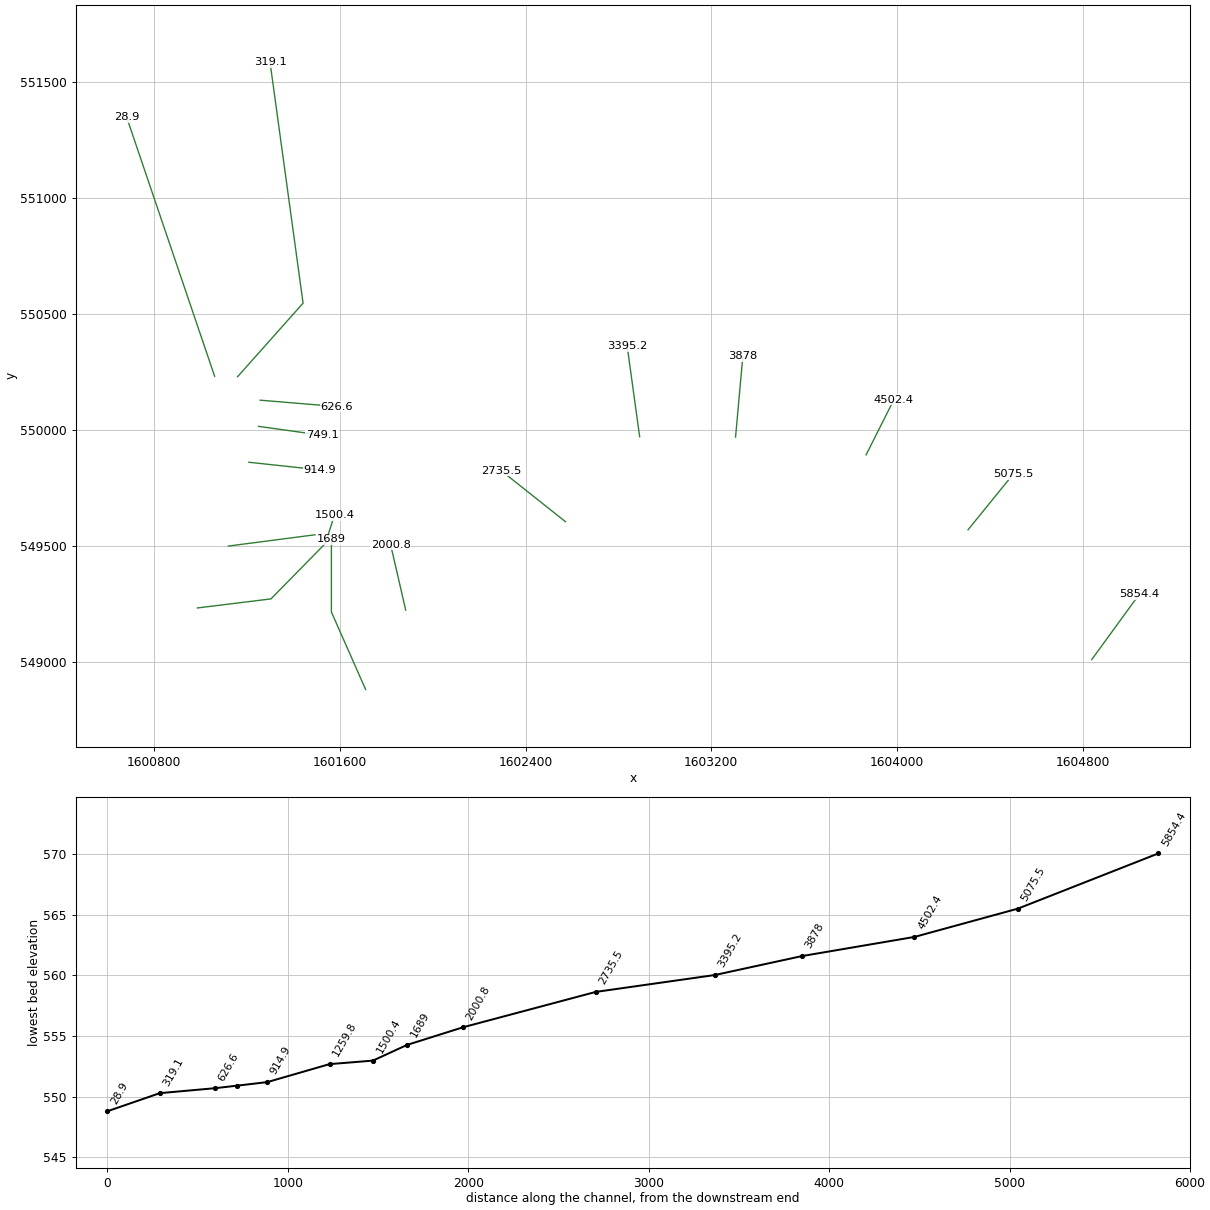
HEC-RAS study SevnmileCr.prj: SevnmileCr

--- SevnmileCr.g01 (geometry) --- (continued)

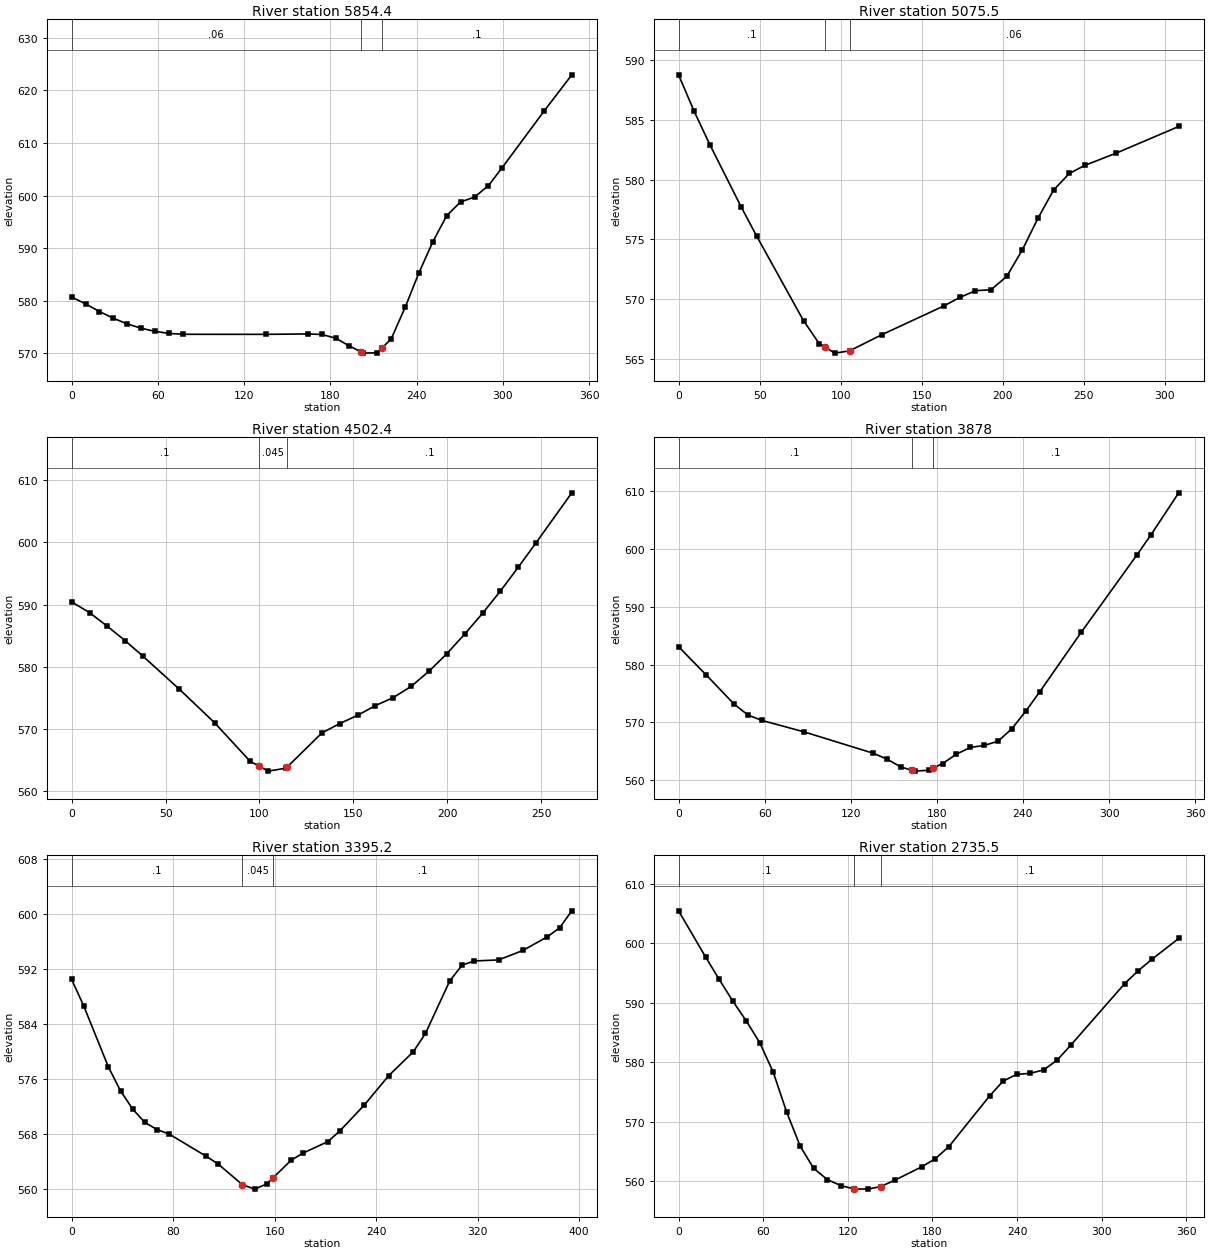
Type RM Length L Ch R = 1 ,5854.4  ,780.1,778.9,777.5
XS GIS Cut Line= 2
     1604839.486      549012.257     1605044.347      549293.507
#Sta/Elev= 29
       0  580.69     9.7   579.4    19.3  577.95      29  576.67    38.7  575.58
    48.3  574.78      58  574.17    67.7  573.79    77.3  573.62   135.3  573.61
   164.3  573.69     174  573.59   183.6  572.89   193.3  571.39     201  570.32
     203  570.04   212.6  570.11     216  571.03   222.3  572.73     232  578.72
   241.6  585.29   251.3  591.21     261  596.19   270.6  598.78   280.3   599.7
     290  601.89   299.6  605.31   328.6  616.01     348  622.94
#Mann= 3 , 0 , 0
       0     .06       0     201    .045       0     216      .1       0
Bank Sta=201,216
XS Rating Curve= 0 ,0
Exp/Cntr=0.3,0.1

Type RM Length L Ch R = 1 ,5075.5  ,568.2,573.1,577.7
XS GIS Cut Line= 2
       1604306.5      549571.285     1604500.944      549810.869
#Sta/Elev= 23
       0  588.76     9.6  585.71    19.3  582.92    38.6  577.72    48.2  575.27
    77.1   568.2    86.8  566.28    90.5  565.98    96.4  565.49   105.5  565.68
   125.4  567.03   163.9  569.45   173.6  570.15   183.2  570.71   192.8  570.79
   202.5  571.91   212.1  574.12   221.8  576.78   231.4  579.13   241.1  580.51
   250.7  581.19     270  582.21   308.6  584.44
#Mann= 3 , 0 , 0
       0      .1       0    90.5    .045       0   105.5     .06       0
Bank Sta=90.5,105.5
XS Rating Curve= 0 ,0
Exp/Cntr=0.3,0.1

Type RM Length L Ch R = 1 ,4502.4  ,615.7,624.4,632.8
XS GIS Cut Line= 2
     1603867.264      549894.202     1603987.055      550132.049
#Sta/Elev= 26
       0  590.42     9.5  588.69      19  586.49    28.5  584.17      38  581.66
    57.1  576.42    76.1  570.95    95.1  564.72    99.5     564   104.6  563.16
   114.1  563.63   114.5  563.75   133.2   569.3   142.7  570.82   152.2  572.14
   161.7  573.71   171.2     575   180.7   576.8   190.2  579.23   199.7  582.06
   209.2  585.21   218.8  588.59   228.3  592.17   237.8  596.01   247.3  599.96
   266.3  607.99
#Mann= 3 , 0 , 0
       0      .1       0    99.5    .045       0   114.5      .1       0
Bank Sta=99.5,114.5
XS Rating Curve= 0 ,0
Exp/Cntr=0.3,0.1

Type RM Length L Ch R = 1 ,3878    ,476.7,482.8,488.3
XS GIS Cut Line= 2
     1603304.764      549970.591     1603336.014      550317.813
#Sta/Elev= 25
       0   583.1    19.4  578.18    38.7  573.17    48.4  571.28    58.1  570.35
    87.2  568.39   135.6  564.68   145.3  563.66   154.9   562.3   162.4  561.74
   164.6  561.58   174.3  561.73   177.4   562.1     184  562.88   193.7  564.52
   203.4  565.68     213  566.02   222.7  566.76   232.4  568.94   242.1  571.99
   251.8  575.32   280.8  585.65   319.6  599.02   329.3  602.47   348.6  609.72
#Mann= 3 , 0 , 0
       0      .1       0   162.4    .045       0   177.4      .1       0
Bank Sta=162.4,177.4
XS Rating Curve= 0 ,0
Exp/Cntr=0.3,0.1

Type RM Length L Ch R = 1 ,3395.2  ,642.4,659.7,677
XS GIS Cut Line= 2
     1602891.569      549972.327      1602837.75      550362.952
#Sta/Elev= 30
       0  590.46     9.6  586.58    28.8  577.82    38.5  574.29    48.1  571.64
    57.7   569.7    67.3  568.67    76.9  568.01   105.8  564.82   115.4  563.68
   134.6  560.66   144.3  560.02   153.9  560.79     159   561.7   173.1  564.23
   182.7  565.28     202  566.92   211.6   568.5   230.8  572.25     250  576.51
   269.3  579.96   278.9  582.62   298.1  590.26   307.8  592.54   317.4  593.15
   336.6   593.3   355.8  594.68   375.1  596.67   384.7  597.96   394.3  600.43
#Mann= 3 , 0 , 0
       0      .1       0   134.6    .045       0     159      .1       0
Bank Sta=134.6,159
XS Rating Curve= 0 ,0
Exp/Cntr=0.3,0.1

Type RM Length L Ch R = 1 ,2735.5  ,750.7,734.7,717.8
XS GIS Cut Line= 2
     1602572.125      549606.007     1602294.347      549826.494
#Sta/Elev= 30
       0  605.46    19.2  597.67    28.8  593.91    38.3  590.32    47.9  586.97
    57.5  583.29    67.1  578.31    76.7  571.54    86.3  565.82    95.8  562.12
   105.4  560.25     115  559.22   124.6  558.66   134.2  558.63   143.2  559.06
   153.4  560.14   172.5   562.4   182.1  563.76   191.7   565.8   220.5  574.31
     230  576.78   239.6  577.94   249.2  578.11   258.8  578.69   268.4  580.34
     278  582.84   316.3  593.21   325.9  595.38   335.5  597.29   354.6  600.81
#Mann= 3 , 0 , 0
       0      .1       0   124.6    .045       0   143.2      .1       0
Bank Sta=124.6,143.2
XS Rating Curve= 0 ,0
Exp/Cntr=0.3,0.1

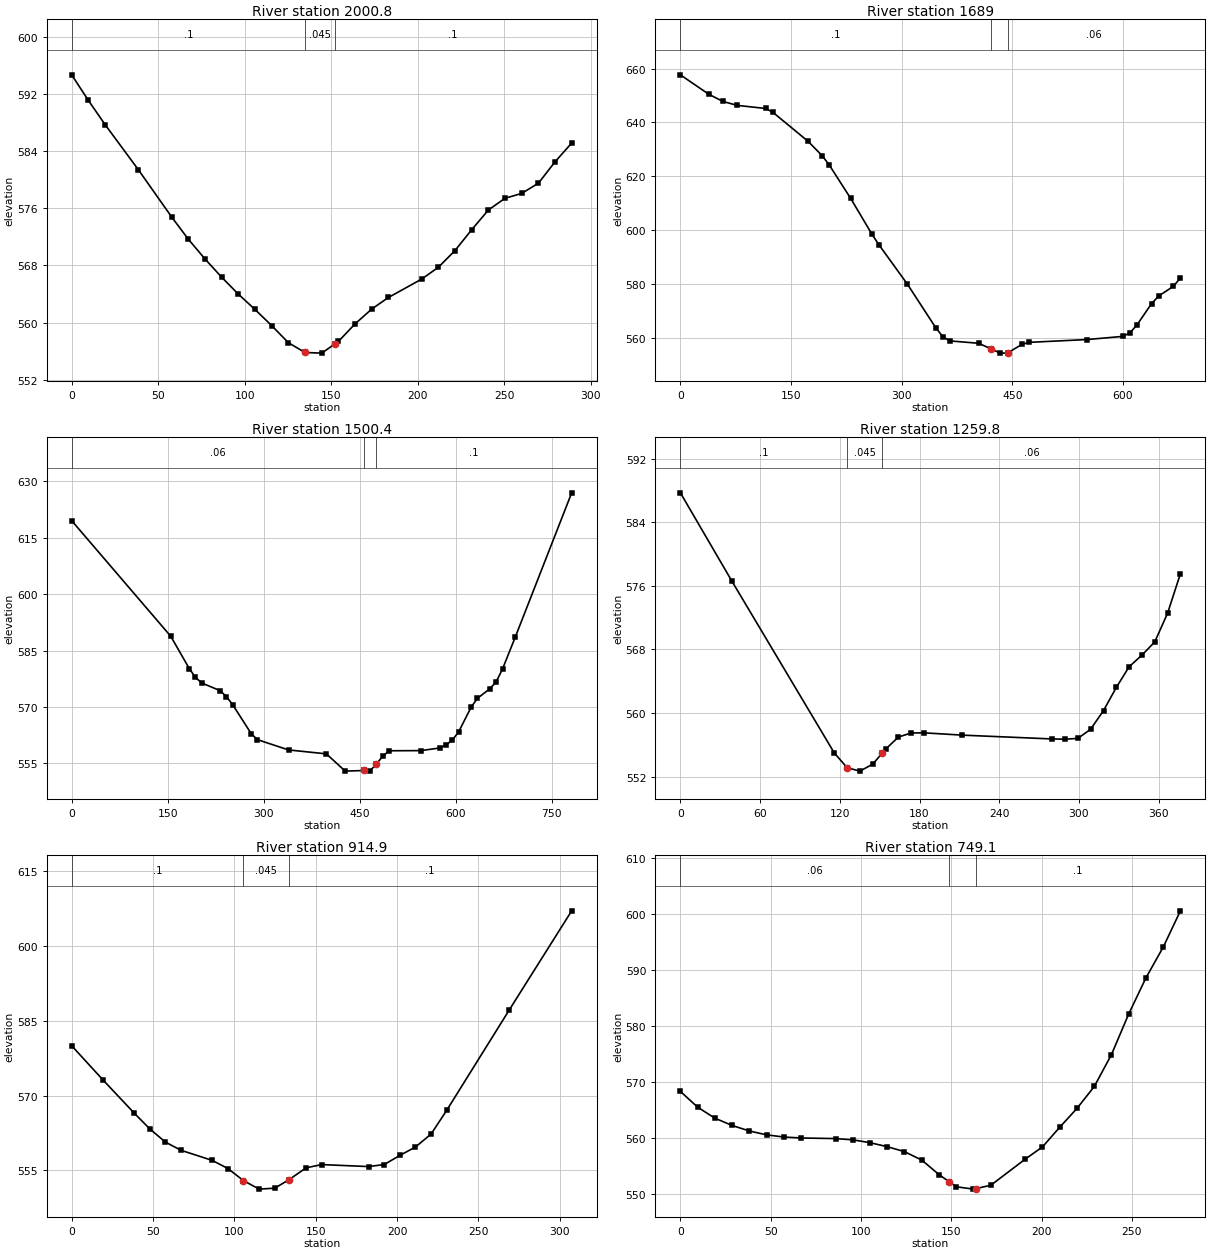
Type RM Length L Ch R = 1 ,2000.8  ,316.8,311.8,306.2
XS GIS Cut Line= 2
     1601883.465      549225.483     1601818.653      549507.049
#Sta/Elev= 29
       0  594.64     9.6  591.08    19.3  587.68    38.5  581.38    57.8  574.75
    67.4  571.65      77   568.9    86.7  566.33    96.3  563.97   105.9  561.83
   115.6  559.56   125.2  557.18   134.8  555.81   144.5  555.72   151.9  556.98
   154.1  557.35   163.7   559.8   173.4  561.89     183   563.5   202.2  566.07
   211.9  567.73   221.5  570.07   231.1  572.97   240.8  575.74   250.4  577.38
     260  578.05   269.7  579.49   279.3  582.48   288.9   585.1
#Mann= 3 , 0 , 0
       0      .1       0   134.8    .045       0   151.9      .1       0
Bank Sta=134.8,151.9
XS Rating Curve= 0 ,0
Exp/Cntr=0.3,0.1

Type RM Length L Ch R = 1 ,1689    ,206,188.6,169.7
XS GIS Cut Line= 3
     1601711.014      548882.917     1601563.444      549217.119
     1601563.444      549529.619
#Sta/Elev= 30
       0  657.67    38.5  650.44    57.7  647.78    76.9  646.32   115.4  645.17
     125  643.82     173  632.98   192.3   627.6   201.9  624.11   230.7  611.81
   259.6  598.47   269.2  594.49   307.6  579.93   346.1  563.72   355.7  560.38
   365.3   558.8   404.4  557.92   421.6  555.77   433.7  554.26   443.5   554.3
     463  557.52   472.8  558.27   550.9   559.3   599.7  560.48   609.5  561.81
   619.2  564.85   638.8   572.7   648.5  575.52   668.1  579.04   677.8   582.2
#Mann= 3 , 0 , 0
       0      .1       0   421.6    .045       0   443.5     .06       0
Bank Sta=421.6,443.5
XS Rating Curve= 0 ,0
Exp/Cntr=0.3,0.1

Type RM Length L Ch R = 1 ,1500.4  ,255.5,240.5,224.7
XS GIS Cut Line= 4
     1600986.187       549234.48     1601303.028      549273.542
     1601537.403      549512.257     1601576.465      549633.785
#Sta/Elev= 30
       0  619.52   154.8  588.81   183.8  580.22   193.5  577.87   203.2  576.39
   232.2  574.34   241.8  572.76   251.5  570.65   280.5  562.95   290.2  561.34
   338.9   558.6     398  557.56   427.5  552.97     457  553.14   466.8  553.11
   475.9   554.8   486.5  557.01   496.4  558.38   545.6  558.42   575.1  559.12
   584.9  559.91   594.7  561.18   604.6  563.36   624.3  569.97   634.1  572.31
   653.8  574.89   663.6  576.77   673.4  580.14   693.1  588.52   781.4  626.91
#Mann= 3 , 0 , 0
       0     .06       0     457    .045       0   475.9      .1       0
Bank Sta=457,475.9
XS Rating Curve= 0 ,0
Exp/Cntr=0.3,0.1

Type RM Length L Ch R = 1 ,1259.8  ,349.5,344.9,339
XS GIS Cut Line= 2
     1601119.286      549501.086      1601492.55      549549.697
#Sta/Elev= 23
       0  587.71    38.6  576.64   115.8  554.98   125.5  553.11   135.1  552.68
   144.8  553.56     152  554.96   154.4  555.43   164.1  556.97   173.7  557.48
   183.4   557.5   212.3  557.21   279.9  556.73   289.6   556.7   299.2   556.8
   308.8  557.95   318.5   560.3   328.2  563.23   337.8  565.82   347.5  567.29
   357.1  568.95   366.8  572.58   376.4  577.54
#Mann= 3 , 0 , 0
       0      .1       0   125.5    .045       0     152     .06       0
Bank Sta=125.5,152
XS Rating Curve= 0 ,0
Exp/Cntr=0.3,0.1

Type RM Length L Ch R = 1 ,914.9   ,166.4,165.8,165.1
XS GIS Cut Line= 2
     1601207.828      549862.197     1601513.384      549829.211
#Sta/Elev= 22
       0     580    19.2  573.15    38.4  566.48      48   563.3    57.6  560.65
    67.2     559    86.4  556.97      96  555.34   105.6  552.91   115.2   551.2
   124.8  551.39   133.4  553.06   144.1  555.48   153.7  556.13   182.5  555.73
   192.1  556.14   201.7  557.97   211.3  559.66   220.9  562.27   230.5  567.03
   268.9  587.17   307.3   607.1
#Mann= 3 , 0 , 0
       0      .1       0   105.6    .045       0   133.4      .1       0
Bank Sta=105.6,133.4
XS Rating Curve= 0 ,0
Exp/Cntr=0.3,0.1

Type RM Length L Ch R = 1 ,749.1   ,121.2,122.5,123.7
XS GIS Cut Line= 2
     1601249.551      550016.751     1601523.798      549978.536
#Sta/Elev= 30
       0  568.37     9.6  565.54    19.1  563.59    28.6  562.29    38.2   561.3
    47.7  560.61    57.3  560.22    66.8  560.05    85.9  559.94    95.5  559.72
     105  559.21   114.6  558.49   124.1  557.61   133.7  556.09   143.2  553.51
   148.7  552.26   152.8  551.33   162.3  550.91   163.7  551.01   171.9   551.6
     191  556.28   200.5  558.45   210.1  561.98   219.6  565.33   229.2  569.25
   238.7  574.94   248.2  582.16   257.8  588.66   267.4  594.17   276.9  600.64
#Mann= 3 , 0 , 0
       0     .06       0   148.7    .045       0   163.7      .1       0
Bank Sta=148.7,163.7
XS Rating Curve= 0 ,0
Exp/Cntr=0.3,0.1

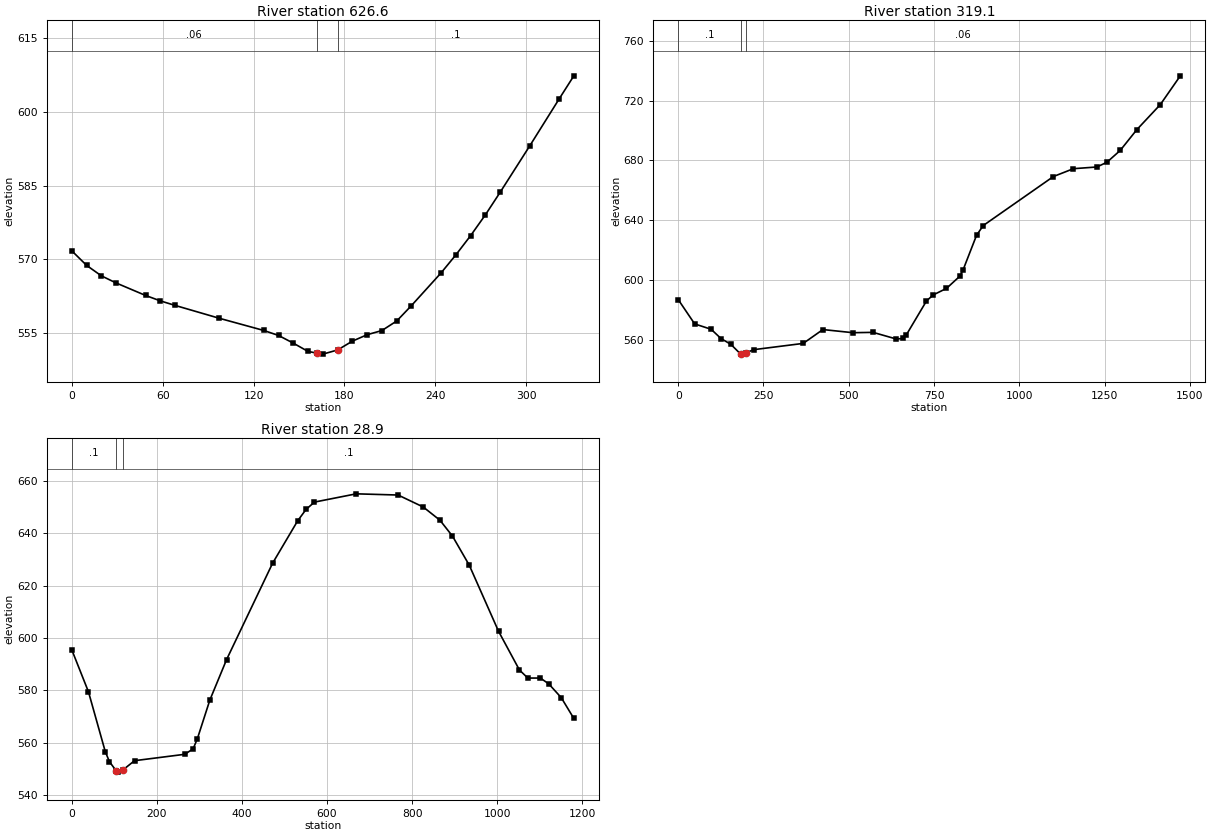
Type RM Length L Ch R = 1 ,626.6   ,286.3,307.5,328.5
XS GIS Cut Line= 2
     1601256.439      550129.558     1601586.739      550102.172
#Sta/Elev= 28
       0  571.74     9.8  568.77    19.5  566.65    29.2   565.2    48.7  562.65
    58.5  561.54    68.2  560.62    97.5  557.99   126.7  555.52   136.5   554.5
   146.2  552.94     156  551.24   161.7  550.92   165.7   550.7   175.5  551.55
   185.2  553.34     195  554.66   204.7   555.5   214.5  557.45   224.2  560.58
   243.7  567.22   253.4  570.86   263.2   574.8     273  579.06   282.7  583.63
   302.2  593.06   321.7  602.67   331.4  607.37
#Mann= 3 , 0 , 0
       0     .06       0   161.7    .045       0   175.5      .1       0
Bank Sta=161.7,175.5
XS Rating Curve= 0 ,0
Exp/Cntr=0.3,0.1

Type RM Length L Ch R = 1 ,319.1   ,265.2,290.2,313.6
XS GIS Cut Line= 3
     1601159.217      550230.686     1601441.335      550547.527
     1601299.006      551585.799
#Sta/Elev= 30
       0  586.81    48.2  570.52    96.4  566.95   125.3  560.75   154.3  556.85
   183.1  550.29   198.1  551.17   221.8  553.29   366.4  557.47   424.2  566.75
   512.4  564.64   571.2  564.87   639.7   560.4   659.3  560.81   669.1  563.29
   727.9   585.9   747.4  589.92   786.6  594.32   825.8  602.51   835.6  606.93
   874.8  629.93   894.4  636.43    1100  669.24  1158.8  674.51  1227.4  675.64
  1256.8  678.78  1295.9  686.71  1344.9  700.71  1413.5  717.43  1472.2  736.71
#Mann= 3 , 0 , 0
       0      .1       0   183.1    .045       0   198.1     .06       0
Bank Sta=183.1,198.1
XS Rating Curve= 0 ,0
Exp/Cntr=0.3,0.1

Type RM Length L Ch R = 1 ,28.9    ,28.8,28.9,29
XS GIS Cut Line= 2
     1601060.476      550232.205     1600680.828      551349.767
#Sta/Elev= 30
       0  595.55    39.3  579.46    78.7  556.66    88.5   552.8   104.9   549.2
   108.2   548.8   119.9  549.59   147.5  553.17   265.6  555.61   285.2  557.68
   295.1  561.48   324.6  576.33   363.9  591.78   472.1  628.61   531.1  644.82
   550.8  649.17   570.5  651.96   668.8  655.12   767.2  654.66   826.2  650.09
   865.5  645.04     895  638.96   934.4  627.87  1003.2  602.63  1052.4  587.82
  1072.1  584.74  1101.6  584.74  1121.3  582.52  1150.8  577.23  1180.3   569.3
#Mann= 3 , 0 , 0
       0      .1       0   104.9    .045       0   119.9      .1       0
Bank Sta=104.9,119.9
XS Rating Curve= 0 ,0
Exp/Cntr=0.3,0.1

Chan Stop Cuts=-1
Use User Specified Reach Order=0
Composite Channel Slope=5